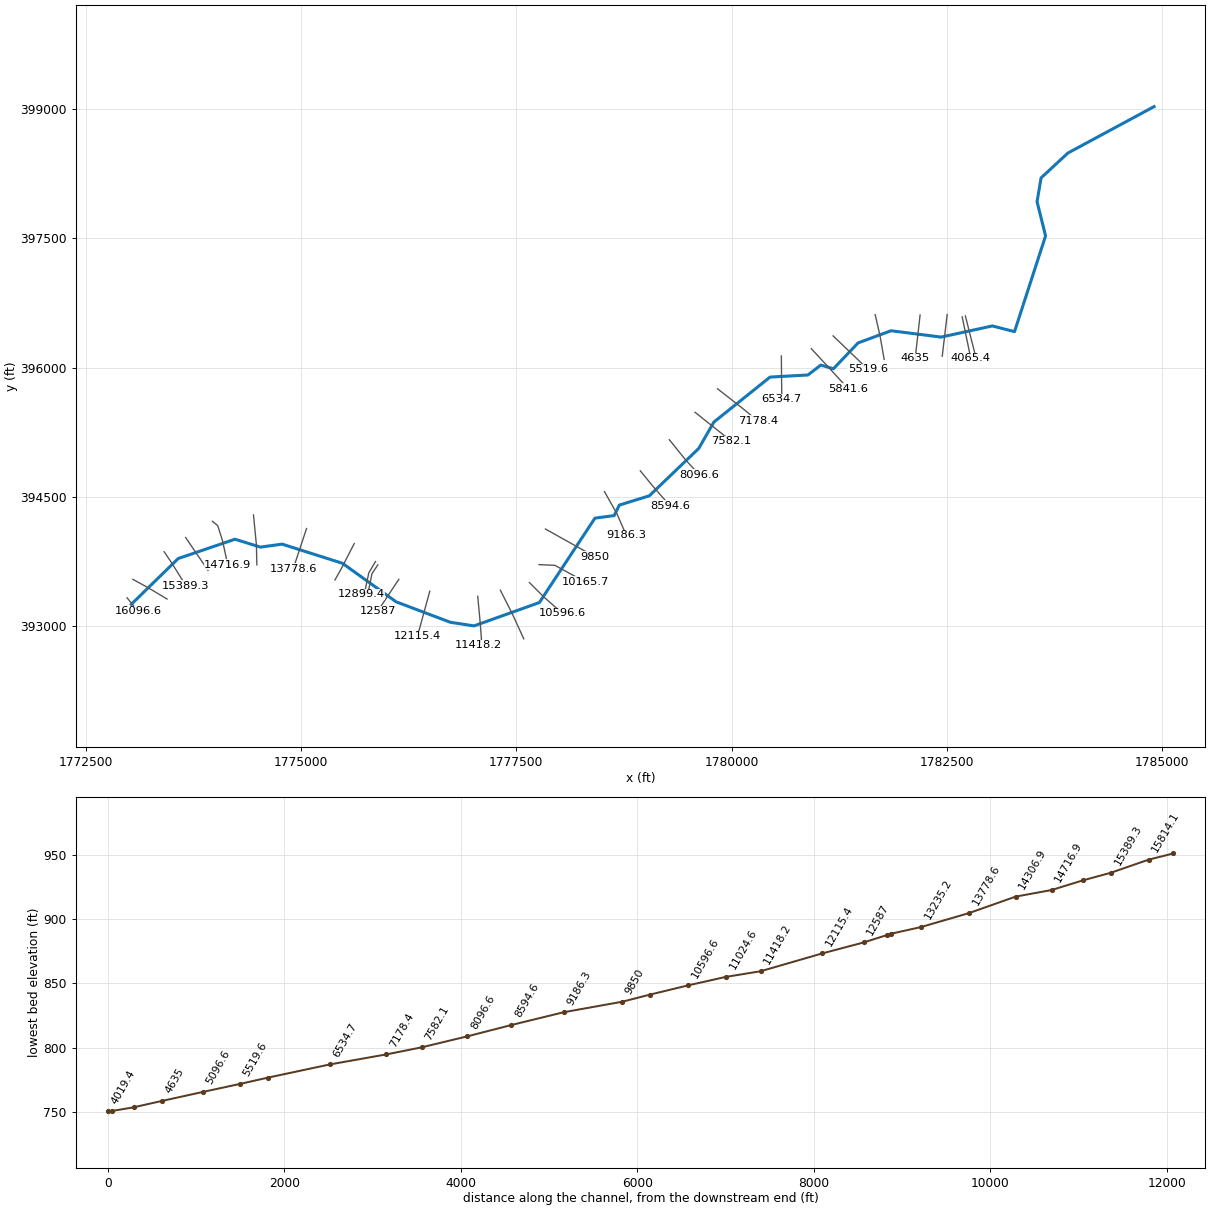
--- SANDLICKCK.prj (project) ---

Proj Title=SANDLICKCK
Current Plan=p01
Default Exp/Contr=0,0
English Units
Geom File=g01
Flow File=f01
Plan File=p01
BEGIN DESCRIPTION:
END DESCRIPTION:
DSS Export Rating Curves= 0
DSS Export Rating Curve Sorted= 0
DSS Export Volume Flow Curves= 0
DXF OffsetX= 0
DXF OffsetY= 0
DXF ScaleX= 0
DXF ScaleY= 0

--- SANDLICKCK.p01 (plan) ---

Plan Title=Floodplain
Program Version=4.00
Geom File=g01
Flow File=f01
K Sum by GR=0
Std Step Tol=0.01
Critical Tol=0.01
Num of Std Step Trials=20
Max Error Tol=0.3
Flow Tol Ratio=0.001
Split Flow NTrial=30
Split Flow Tol=0.02
Split Flow Ratio=0.02
Log Output Level=0
Friction Slope Method=1
Unsteady Friction Slope Method=2
Unsteady Bridges Friction Slope Method=1
Global Log Level=0
CheckData=False
Run HTab=0
Run UNet=0
Run PostProcess=0
UNET Theta=0
UNET Theta Warmup=0
UNET ZTol=0
UNET ZSATol=0
UNET MxIter=0
UNET MaxInSteps=0
UNET DtIC=0
UNET DtMin=0
UNET MaxCRTS=0
UNET WFStab=0
UNET SFStab=0
UNET WFX=0
UNET SFX=0
UNET DSS MLevel=0
UNET DZMax Abort=0
UNET Convert EG Bridges=0
UNET Use Existing IB Tables=0
UNET Froude Limit=0
UNET Froude Power=0
Write IC File=0
Echo Input=False
Echo Output=False
Write Detailed=0

--- SANDLICKCK.f01 (steady flow) ---

Flow Title=NFF Regression Equation
Program Version=4.10
Number of Profiles= 1
Profile Names=P100yr
River Rch & RM=SANDLICKCK,Main            ,16096.6
 914.009
River Rch & RM=SANDLICKCK,Main            ,15389.3
926.4733
River Rch & RM=SANDLICKCK,Main            ,14716.9
1113.759
River Rch & RM=SANDLICKCK,Main            ,11418.2
1159.066
River Rch & RM=SANDLICKCK,Main            ,10165.7
1283.526
River Rch & RM=SANDLICKCK,Main            ,9850
1436.912
River Rch & RM=SANDLICKCK,Main            ,8594.6
1467.578
River Rch & RM=SANDLICKCK,Main            ,1078.4
1904.725
River Rch & RM=SANDLICKCK,Main            ,1078.4
1629.541
River Rch & RM=SANDLICKCK,Main            ,635
1907.547
River Rch & RM=SANDLICKCK,Main            ,423
1911.925
Boundary for River Rch & Prof#=SANDLICKCK,Main            , 1
Up Type= 0
Dn Type= 3
Dn Slope=0.006688
DSS Import GetInterval= 0
DSS Import GetPeak= 0
DSS Import FillOption= 0

--- SANDLICKCK.g01 (geometry) ---

Geom Title=USGS 10m DEM
Program Version=4.10

River Reach=SANDLICKCK      ,Main
Reach XY= 30
     1773030.113      393254.321     1773574.576      393785.161
     1774234.437       394009.12     1774529.298      393917.453
     1774780.826      393952.175      1775481.66      393729.953
     1776105.591      393282.774     1776735.799      393045.621
     1777009.758      393003.955     1777768.091      393274.788
      1778413.23      394253.521     1778636.321      394283.035
     1778696.737      394404.909     1779044.827      394512.548
     1779618.265      395061.507      1779794.48       395367.93
     1780446.737      395889.545     1780886.494       395913.85
     1781035.678      396028.594     1781182.501      395985.812
     1781468.092      396285.291     1781850.904      396426.784
     1782432.501         396353.     1783027.119       396482.34
     1783284.932      396416.368     1783645.392      397526.138
     1783546.651      397923.816     1783593.308      398199.423
     1783904.723       398487.51     1784905.157      399025.921

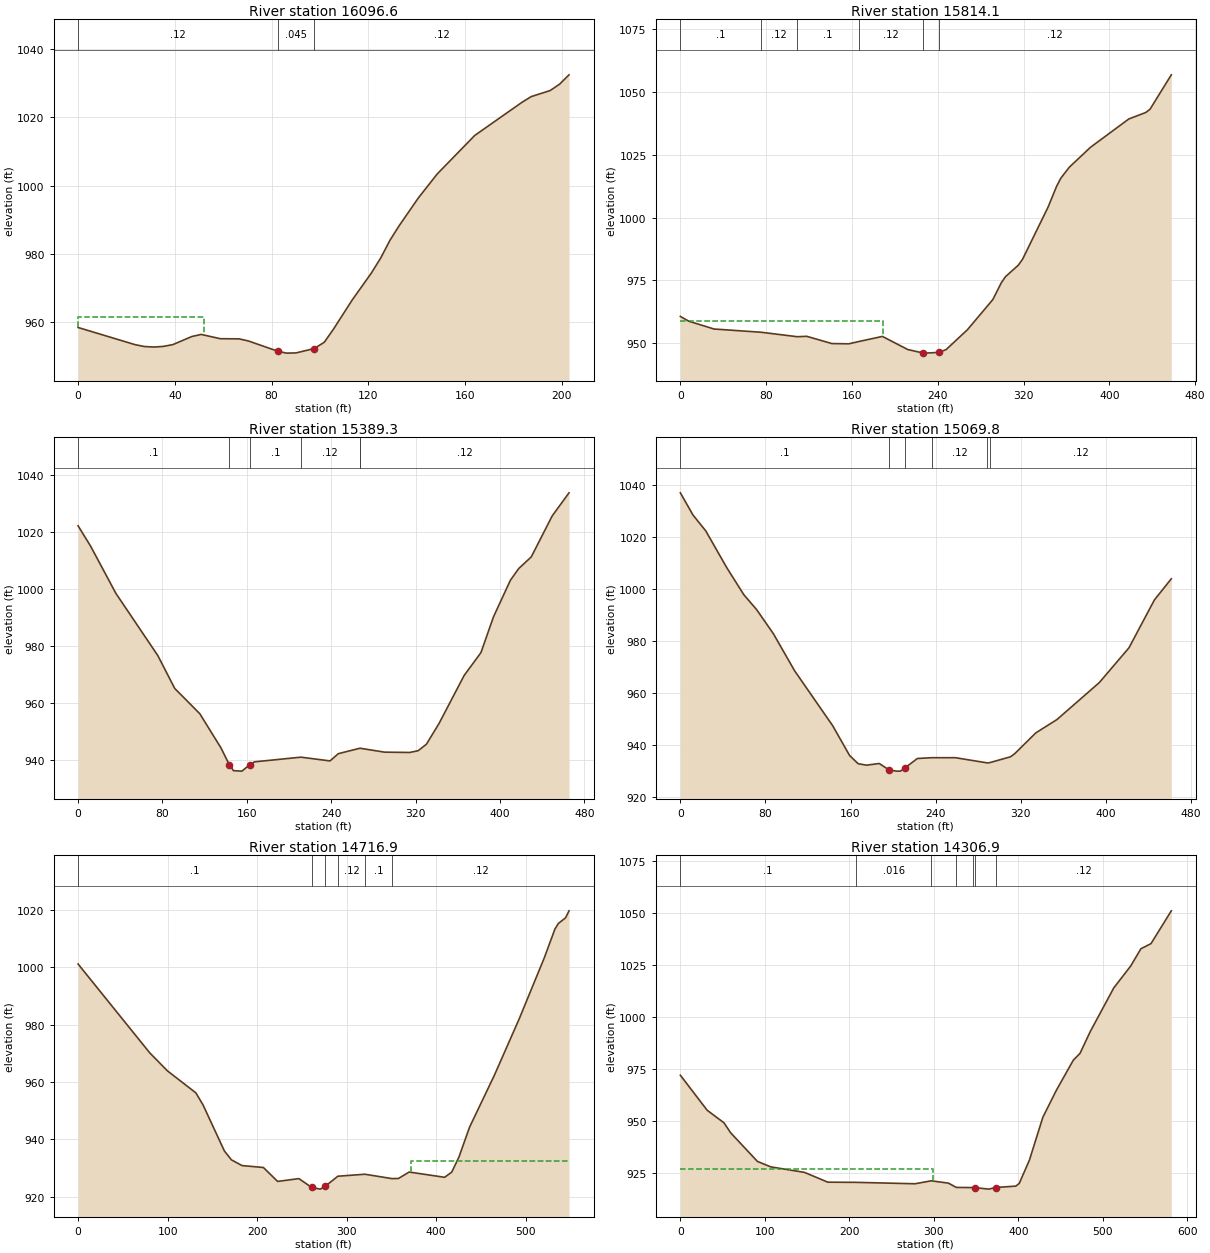
Type RM Length L Ch R = 1 ,16096.6 ,274.6,282.5,289.7
XS GIS Cut Line= 3
     1772980.358      393329.826     1773037.934      393260.552
     1773108.967      393172.803
#Sta/Elev= 30
       0  958.53    23.5  953.52    27.4  952.96    31.3  952.81    35.2  952.99
    39.2  953.52      47  955.88    50.9   956.5    58.8  955.25    66.6   955.2
    70.5  954.57    82.6  951.58    86.2  951.03    90.1  951.09    97.6  952.36
   101.8  954.21   105.6  958.04   113.4  966.63   121.2  974.38   125.1  978.81
     129  984.09   132.9  988.43   140.7  996.42   148.5 1003.43     164 1014.69
   183.5 1024.37   187.4 1026.07   195.2 1027.83   199.1  1029.7     203 1032.43
#Mann= 3 ,-1 , 0
       0     .12       0    82.6    .045       0    97.6     .12       0
#XS Ineff= 2 , 0
           52.01  961.67
Permanent Ineff=
       F       F
Bank Sta=82.6,97.6
XS Rating Curve= 0 ,0
Exp/Cntr=0.3,0.1

Type RM Length L Ch R = 1 ,15814.1 ,432.2,424.8,416.2
XS GIS Cut Line= 3
     1773048.361      393543.601     1773220.558      393449.478
     1773445.188      393315.467
#Sta/Elev= 30
       0  960.72     7.8  958.83    31.4  955.72   75.31954.4308  108.97952.6628
   117.8  952.82   141.3  949.94     157  949.84  166.51950.7509   188.4  952.78
   212.1  947.56   226.1  946.22     228  946.14   241.1  946.43   247.8  947.54
   267.6  955.39   291.4  967.42   299.3   974.1   303.2  976.51   315.1  981.05
   319.1  983.42   342.9 1004.14   350.8 1012.36   354.8 1015.63   362.7 1019.98
   382.5 1027.92   418.2 1039.15     434 1041.72     438 1043.03   457.8 1056.68
#Mann= 6 ,-1 , 0
       0      .1       0   75.31     .12       0  108.97      .1       0
  166.51     .12       0   226.1    .045       0   241.1     .12       0
#XS Ineff= 2 , 0
          189.37  958.71
Permanent Ineff=
       F       F
Bank Sta=226.1,241.1
XS Rating Curve= 0 ,0
Exp/Cntr=0.3,0.1

Type RM Length L Ch R = 1 ,15389.3 ,318.8,319.4,319.8
XS GIS Cut Line= 3
     1773411.315      393864.306     1773500.451      393732.354
     1773662.165      393472.358
#Sta/Elev= 30
       0 1022.26    11.9  1015.1    35.8  998.54    75.6  976.65    91.6  965.12
   115.4  956.22   135.4  944.25   143.3  938.35   147.3  936.21   155.3  936.05
   162.8  938.31   167.2  939.31   211.3 940.954   238.8  939.64   246.7  942.18
  266.88944.0717  267.22944.0981   290.5  942.72   314.3  942.61   322.3  943.21
   330.2   945.5   342.2  952.81     366  969.68   381.9   977.7   393.8  990.27
   409.8 1003.11   417.7 1007.23   429.6 1011.33   449.5 1025.77   465.4 1033.85
#Mann= 6 ,-1 , 0
       0      .1       0   143.3    .045       0   162.8      .1       0
   211.3     .12       0  266.88      .1       0  267.22     .12       0
Bank Sta=143.3,162.8
XS Rating Curve= 0 ,0
Exp/Cntr=0.3,0.1

Type RM Length L Ch R = 1 ,15069.8 ,360,353,344.1
XS GIS Cut Line= 2
     1773660.838      394028.922     1773920.623      393647.512
#Sta/Elev= 30
       0 1037.06    11.9 1028.52    23.9 1022.42    43.8 1008.17    59.7  997.88
    71.6  992.22    87.5  982.87   107.4  968.66   143.2  947.54   159.1  936.09
   167.1  932.94     175  932.37     187  933.01     196   930.6   202.9  930.08
   206.9  930.08     211  931.27   222.8  934.94  236.15935.2343   258.6  935.24
  288.61933.2408  290.74933.3265   310.3  935.59   314.3  936.78   334.2   944.8
   354.1  949.93   393.8  964.11   421.7  977.48   445.6  995.88   461.5 1004.02
#Mann= 6 ,-1 , 0
       0      .1       0     196    .045       0     211      .1       0
  236.15     .12       0  288.61      .1       0  290.74     .12       0
Bank Sta=196,211
XS Rating Curve= 0 ,0
Exp/Cntr=0.3,0.1

Type RM Length L Ch R = 1 ,14716.9 ,414.1,409.9,406
XS GIS Cut Line= 4
     1773971.616      394217.443     1774033.546      394166.707
      1774088.94      393992.813     1774149.905      393713.501
#Sta/Elev= 30
       0  1001.2    80.1  970.17    99.9  963.88   131.6  956.21   139.6     952
   163.4  935.95   171.3  932.83   183.2  930.83     207  930.16   222.9   925.3
   246.7  926.28   260.8  923.23   270.5  922.61   275.8  923.54  290.18 927.113
  320.41927.8096  350.64926.2808   357.9  926.33   369.8  928.58   409.5  926.74
   417.4  928.56   425.4  933.77   437.3  944.24   465.1  962.42   492.9  982.16
   520.7  1003.3   532.6 1013.36   536.5 1015.37   544.5 1017.32   548.4 1019.77
#Mann= 6 ,-1 , 0
       0      .1       0   260.8    .045       0   275.8      .1       0
  290.18     .12       0  320.41      .1       0  350.64     .12       0
#XS Ineff= 2 , 0
                           371.4          932.26
Permanent Ineff=
       F       F
Bank Sta=260.8,275.8
XS Rating Curve= 0 ,0
Exp/Cntr=0.3,0.1

Type RM Length L Ch R = 1 ,14306.9 ,537.7,528.4,519
XS GIS Cut Line= 3
     1774448.534      394290.761     1774482.361      393947.314
     1774487.874      393711.532
#Sta/Elev= 30
       0   972.2    31.7  955.36    51.6  949.33    59.5  944.53    91.2  930.77
   107.1  928.13   146.8   925.5   174.5  920.78  207.79920.6959   277.7  920.02
  296.83921.4327   317.3  920.32  326.51918.2653   346.9  918.17   349.1  918.14
   365.1  917.44   373.1  918.22   397.1   918.9   401.1  920.21   413.1  931.39
     429  951.98     445  964.97     465   979.4     473  982.72     485  993.09
     513 1014.21     533  1024.7     545 1032.97     557 1035.45     581 1051.21
#Mann= 7 ,-1 , 0
       0      .1       0  207.79    .016       0  296.83      .1       0
  326.51     .12       0   346.9     .12       0   349.1    .045       0
   373.1     .12       0
#XS Ineff= 2 , 0
          299.15  927.24
Permanent Ineff=
       F       F
Bank Sta=349.1,373.1
XS Rating Curve= 0 ,0
Exp/Cntr=0.3,0.1

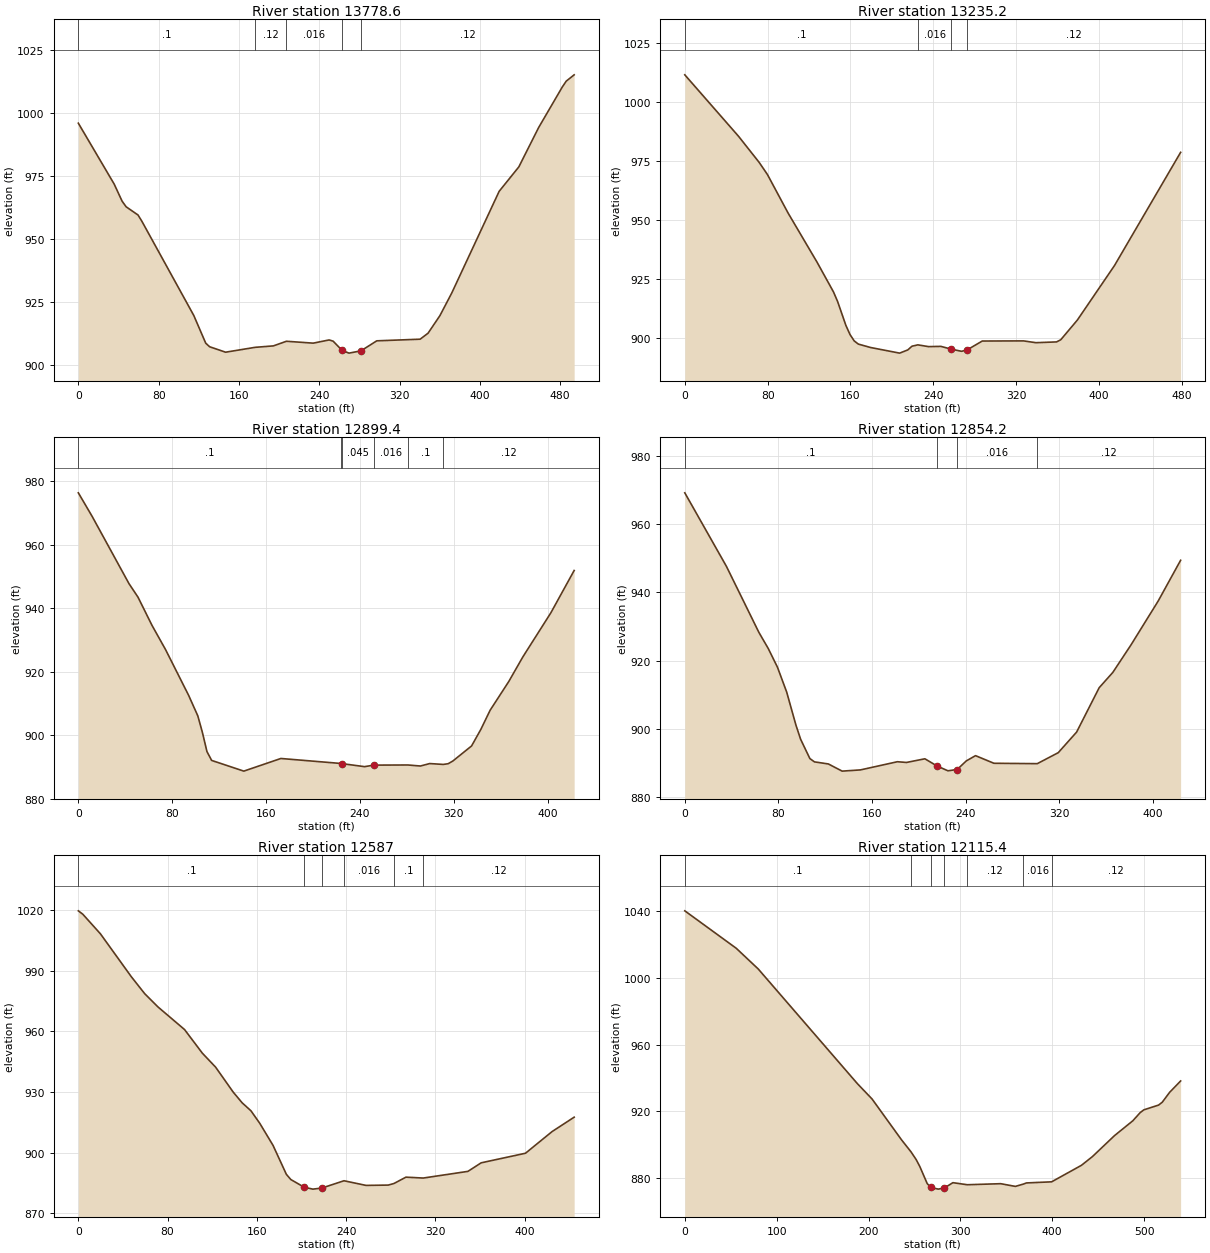
Type RM Length L Ch R = 1 ,13778.6 ,546.9,543.4,539.8
XS GIS Cut Line= 3
     1775064.856       394133.02     1774976.181      393865.821
     1774909.286      393664.252
#Sta/Elev= 30
       0   995.9    35.7  971.74    43.6  964.96    47.6  962.73    59.5  959.45
    63.4  956.91     115   919.6   126.9   908.6   130.8  907.18   146.7  905.02
  176.17906.9514   194.3  907.52  207.29909.3572     234  908.61   249.8  909.88
   253.8   909.4   262.8  905.72   269.6  904.65   281.5  905.55   297.3  909.53
   340.5  910.18   348.4  912.57   360.2  919.54     372  928.53   419.2  968.86
   438.8  978.56   458.5  994.15   482.1 1010.27     486 1012.58   493.9 1015.09
#Mann= 5 ,-1 , 0
       0      .1       0  176.17     .12       0  207.29    .016       0
   262.8    .045       0   281.5     .12       0
Bank Sta=262.8,281.5
XS Rating Curve= 0 ,0
Exp/Cntr=0.3,0.1

Type RM Length L Ch R = 1 ,13235.2 ,328.9,335.7,343.4
XS GIS Cut Line= 3
     1775618.752      393959.151     1775465.273      393661.225
     1775394.315      393536.173
#Sta/Elev= 30
       0 1011.42    51.9  985.45    71.8  974.43    79.8   969.3    99.7  953.06
   127.7  932.27   143.6  919.68   147.6  915.61   155.6  905.51   159.6  901.64
   163.6  898.98   167.6  897.62   179.5  896.17   207.5   893.8   215.4  895.16
   219.4  896.72  225.08897.2934   235.4  896.55   247.4  896.65   257.5  895.46
   267.3  894.57   272.5  895.12   287.3  898.91   327.2  898.97   339.1  898.21
   359.1  898.54   363.1  899.44   379.1  907.74     415  930.79   478.9  978.66
#Mann= 4 ,-1 , 0
       0      .1       0  225.08    .016       0   257.5    .045       0
   272.5     .12       0
Bank Sta=257.5,272.5
XS Rating Curve= 0 ,0
Exp/Cntr=0.3,0.1

Type RM Length L Ch R = 1 ,12899.4 ,44.8,45.3,45.5
XS GIS Cut Line= 4
       1775865.1      393750.151     1775787.694      393618.491
     1775747.912      393432.442     1775697.131      393371.245
#Sta/Elev= 30
       0  976.29    11.8  968.86    43.1  947.75    50.9  943.42    62.7  934.63
    74.4   926.9      94  912.54   101.8  906.11   105.7  900.92   109.6  894.86
   113.6  892.07     141   888.7   172.6  892.68   223.8  891.11  224.55891.0627
   243.9  890.11   251.8  890.59  280.82890.6337   291.5  890.31   299.4  891.08
  311.02890.8107   315.2  891.04   319.2   891.9   335.1  896.63     343  901.84
   350.9  907.86   366.8  916.91   378.8  924.66   402.6   938.5   422.5  951.84
#Mann= 6 ,-1 , 0
       0      .1       0   223.8    .016       0  224.55    .045       0
   251.8    .016       0  280.82      .1       0  311.02     .12       0
Bank Sta=224.55,251.8
XS Rating Curve= 0 ,0
Exp/Cntr=0.3,0.1

Type RM Length L Ch R = 1 ,12854.2 ,276.7,267.2,256.2
XS GIS Cut Line= 4
     1775892.443      393711.088     1775824.186        393609.1
     1775781.766      393401.192     1775725.777      393332.182
#Sta/Elev= 30
       0  969.17    35.6  947.63    63.3  928.33    71.3  923.61    79.2  918.12
    87.1  910.82      95  901.16      99  897.02   106.9  891.37   110.8   890.4
   122.7  889.79   134.5  887.69   150.2  888.05   181.7  890.44   189.5  890.23
   205.2   891.3   215.9  889.14   224.9  887.79   232.8  888.16   240.6  890.68
   248.5  892.22   264.2  889.99  301.27889.8756   319.2  893.09   334.9  899.12
   354.2  912.12   365.8  916.57   381.3   924.6   404.5  937.42   423.8  949.42
#Mann= 4 ,-1 , 0
       0      .1       0   215.9    .045       0   232.8    .016       0
  301.27     .12       0
Bank Sta=215.9,232.8
XS Rating Curve= 0 ,0
Exp/Cntr=0.3,0.1

Type RM Length L Ch R = 1 ,12587   ,464.1,471.5,478.5
XS GIS Cut Line= 2
     1776136.137      393543.707     1775889.889      393173.898
#Sta/Elev= 30
       0 1019.53       4 1017.86    19.8 1008.16    47.6  986.85    59.5  978.54
    71.4  971.98    95.2   960.8   111.1  949.15     123  942.23   138.8  929.86
   146.8  924.58   154.7  920.62   162.6  914.43   174.5  903.51   186.4  889.22
   190.4  886.64   202.4  882.82   210.2  881.89   218.2  882.42  238.07886.0292
   257.8  883.73   277.7  883.89  282.75884.6549   293.6  887.81  309.04887.3681
   349.1  890.67     361   894.9   400.7  899.64   424.5  910.34   444.3  917.47
#Mann= 6 ,-1 , 0
       0      .1       0   202.4    .045       0   218.2      .1       0
  238.07    .016       0  282.75      .1       0  309.04     .12       0
Bank Sta=202.4,218.2
XS Rating Curve= 0 ,0
Exp/Cntr=0.3,0.1

Type RM Length L Ch R = 1 ,12115.4 ,688.9,697.3,704.6
XS GIS Cut Line= 2
     1776495.682       393405.73     1776352.668      392885.221
#Sta/Elev= 30
       0 1040.33      56 1017.86      80  1005.4   187.9  936.62   203.9  927.39
   235.9  902.94   246.2895.7482   251.9  891.05   255.9  886.84   263.9  876.66
   267.7   874.4   275.9  873.32   282.7  874.06   291.9  877.19  307.46875.9556
   343.9  876.58   359.9  874.96  368.72876.3622   371.9  877.03  399.35877.6993
   431.8   887.6   443.8  892.85   467.8  905.42   487.8  914.35   495.8  919.25
   499.8  920.91   515.8  923.76   519.8  925.47   527.8  931.39   539.8  938.22
#Mann= 7 ,-1 , 0
       0      .1       0   246.2     .12       0   267.7    .045       0
   282.7      .1       0  307.46     .12       0  368.72    .016       0
  399.35     .12       0
Bank Sta=267.7,282.7
XS Rating Curve= 0 ,0
Exp/Cntr=0.3,0.1

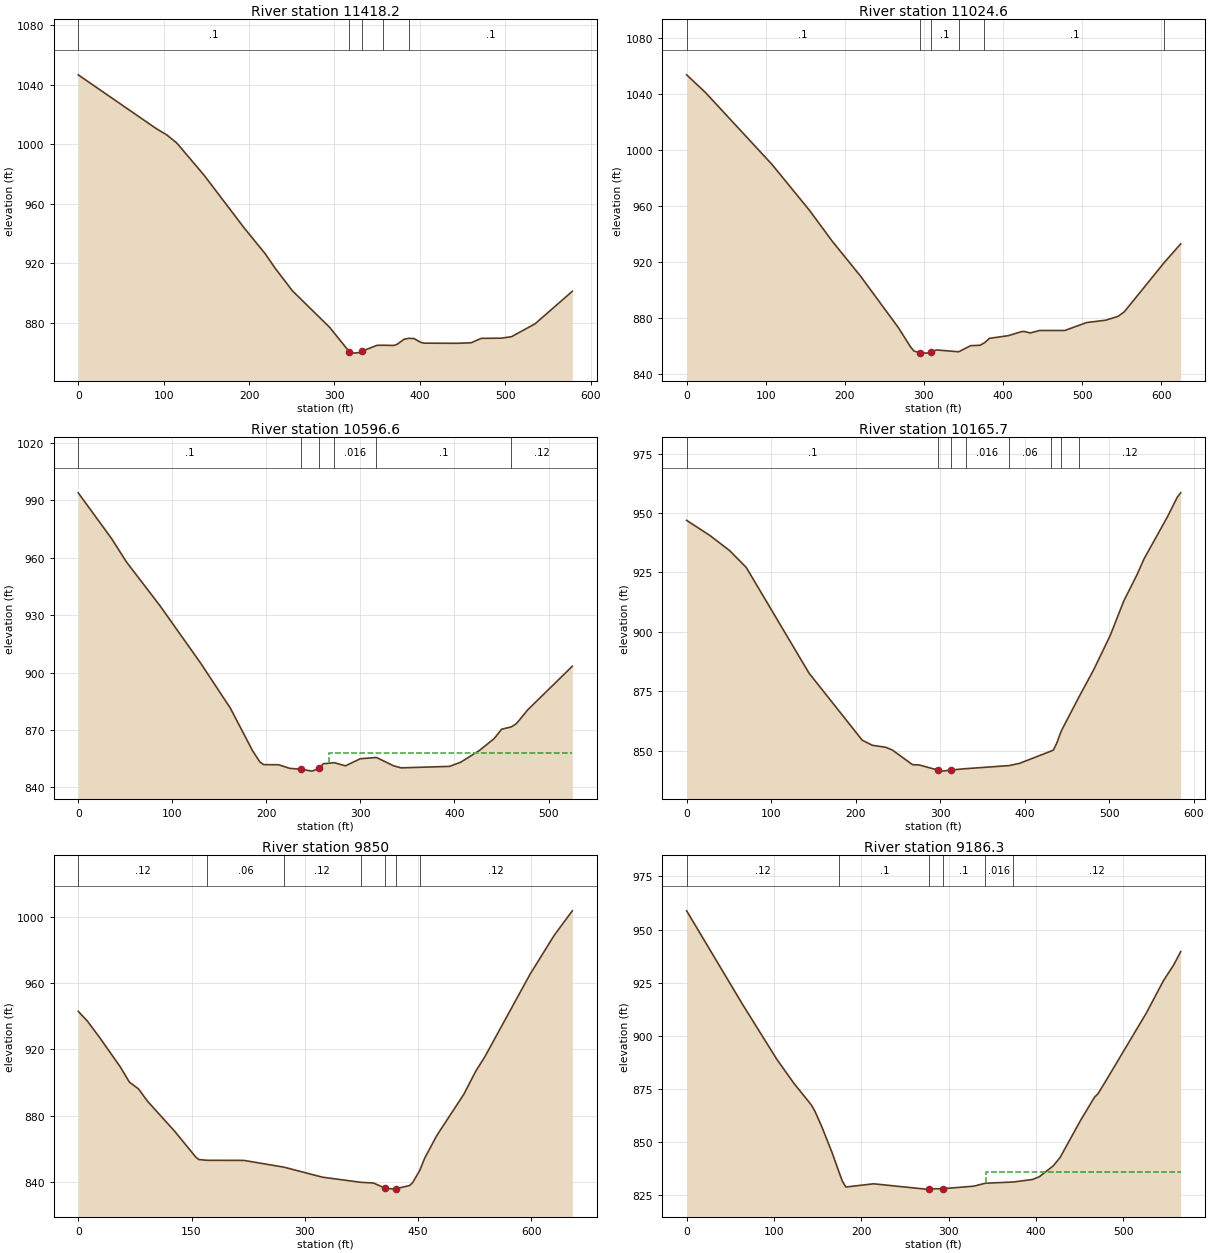
Type RM Length L Ch R = 1 ,11418.2 ,384.4,393.6,401.5
XS GIS Cut Line= 4
     1777052.544      393347.009     1777081.175      393037.878
     1777095.964      392845.416     1777056.932      392781.227
#Sta/Elev= 30
       0 1046.51    91.5 1010.32   103.5 1006.23   115.4  1000.7   147.3  979.12
     195  943.13   218.9  926.34   230.8   916.4   250.8  901.41   294.5   876.8
   317.6  860.33   322.3   859.5   330.2   859.9   332.6  860.88   349.8  864.73
  357.37864.8069   369.5  864.67   373.5  865.45   381.4  868.76  386.99869.4484
   393.2  869.29   401.1  866.75     405  866.21   444.4  866.11   460.2  866.48
     472  869.43   495.6  869.55   507.4  870.54   535.1  879.24   578.6  901.04
#Mann= 5 ,-1 , 0
       0      .1       0   317.6    .045       0   332.6      .1       0
  357.37    .016       0  386.99      .1       0
Bank Sta=317.6,332.6
XS Rating Curve= 0 ,0
Exp/Cntr=0.3,0.1

Type RM Length L Ch R = 1 ,11024.6 ,420.6,428,437.1
XS GIS Cut Line= 3
      1777315.71      393416.889     1777457.786      393135.153
     1777586.872      392854.055
#Sta/Elev= 30
       0 1053.96      24 1041.19   107.8  990.02   155.8  956.82   183.7  935.37
   219.7  910.26   267.6  873.46   283.6   859.2   287.6  856.57   294.5  855.49
   303.6  855.12   309.5  855.74   315.5   857.4  344.05856.0963   359.2  860.45
     371  860.74  376.55862.4809     383  865.69   406.7  867.58   422.6  870.35
   426.6  870.66   434.5  869.53   446.4  871.29   478.1  871.27   505.9  876.99
   529.7  878.61   545.5  881.38   553.5  884.65  604.06919.9193   624.8  933.19
#Mann= 6 ,-1 , 0
       0      .1       0   294.5    .045       0   309.5      .1       0
  344.05    .016       0  376.55      .1       0  604.06     .12       0
Bank Sta=294.5,309.5
XS Rating Curve= 0 ,0
Exp/Cntr=0.3,0.1

Type RM Length L Ch R = 1 ,10596.6 ,424.3,430.9,430.7
XS GIS Cut Line= 3
     1777652.081        393506.7     1777825.379      393334.198
     1778036.737      393149.361
#Sta/Elev= 30
       0  993.94    35.5     970    51.3  957.79    86.8  935.02   130.2  904.91
   161.7  881.46   185.4  859.14   193.2  853.26   197.2  851.91     213  851.86
   224.8  849.97     237   849.5   248.5  848.52   256.4  849.96   260.3  852.35
  272.19852.9406   284.1  851.28   299.9  854.99  317.06 855.663   335.5  851.25
   343.4  850.23   394.8     851   406.7  853.19   426.4  859.26   442.2  865.51
   450.2  870.44  460.37871.6136     466  873.39   477.8  880.48   525.3  903.33
#Mann= 6 ,-1 , 0
       0      .1       0     237    .045       0   256.4      .1       0
  272.19    .016       0  317.06      .1       0  460.37     .12       0
#XS Ineff= 2 , 0
                          266.93           858.1
Permanent Ineff=
       F       F
Bank Sta=237,256.4
XS Rating Curve= 0 ,0
Exp/Cntr=0.3,0.1

Type RM Length L Ch R = 1 ,10165.7 ,315.6,315.7,315.1
XS GIS Cut Line= 3
     1777764.483      393714.585     1777948.297      393706.223
     1778299.937      393514.044
#Sta/Elev= 30
       0  946.91    27.4  940.58    50.9  934.18    70.5  927.11   144.8  882.64
   207.8  854.39   219.7  852.26   235.6  851.42   243.5  850.24   267.3   844.1
   275.3  843.97   297.6  841.79     303  841.38   312.6  841.85  330.08842.4092
  381.86 843.723   394.3   844.7  431.06849.7869     434  850.25   437.9  853.06
  443.45858.3591  464.72 872.886   481.6  883.96   501.4  898.57   517.3  912.97
   533.2   924.2   541.1  930.58   568.9  948.34   580.8  956.76   584.7   958.5
#Mann= 8 ,-1 , 0
       0      .1       0   297.6    .045       0   312.6      .1       0
  330.08    .016       0  381.86     .06       0  431.06      .1       0
  443.45     .08       0  464.72     .12       0
Bank Sta=297.6,312.6
XS Rating Curve= 0 ,0
Exp/Cntr=0.3,0.1

Type RM Length L Ch R = 1 ,9850    ,676.3,663.6,648.9
XS GIS Cut Line= 2
     1777838.712      394127.202     1778410.023      393808.228
#Sta/Elev= 30
       0  942.94      12  937.13    27.9  927.43    55.9  909.32    67.8  900.25
    79.8  896.21    91.8  888.77   127.7  870.69   155.6  855.16   159.6  853.64
  170.84853.1924   219.4  853.12  272.32849.0586   323.2  843.04  373.81839.9435
     391   839.5   406.4   836.4   418.9  835.82   421.4  836.17   438.9  837.99
   442.9  839.76  452.34847.1409   458.8  854.46   474.8  868.08   510.7     893
   526.6  906.99   538.6  915.66   598.5  965.39   630.4  988.75   654.3 1003.48
#Mann= 7 ,-1 , 0
       0     .12       0  170.84     .06       0  272.32     .12       0
  373.81      .1       0   406.4    .045       0   421.4    .016       0
  452.34     .12       0
Bank Sta=406.4,421.4
XS Rating Curve= 0 ,0
Exp/Cntr=0.3,0.1

Type RM Length L Ch R = 1 ,9186.3  ,587.3,591.8,597.2
XS GIS Cut Line= 3
     1778523.948      394561.193     1778667.921       394305.62
     1778777.165      394056.084
#Sta/Elev= 30
       0  958.81    63.4  915.14   103.1  888.94   122.9  877.47   142.7  867.36
   146.7  864.51   154.6  857.21   166.5  844.88  174.91835.1813   178.4  831.29
   182.3  828.66   214.1  830.17   273.5  827.66     278  827.79     293  827.86
   328.9  829.06  341.91830.4376  374.16831.0249     396   832.2   403.9  833.52
   419.7  838.61   427.6  842.58   451.2  860.19     467  870.97     471  872.62
   478.9  877.92   526.3  910.61     546  925.94   557.8  933.41   565.7  939.62
#Mann= 6 ,-1 , 0
       0     .12       0  174.91      .1       0     278    .045       0
     293      .1       0  341.91    .016       0  374.16     .12       0
#XS Ineff= 2 , 0
                          342.57           835.5
Permanent Ineff=
       F       F
Bank Sta=278,293
XS Rating Curve= 0 ,0
Exp/Cntr=0.3,0.1

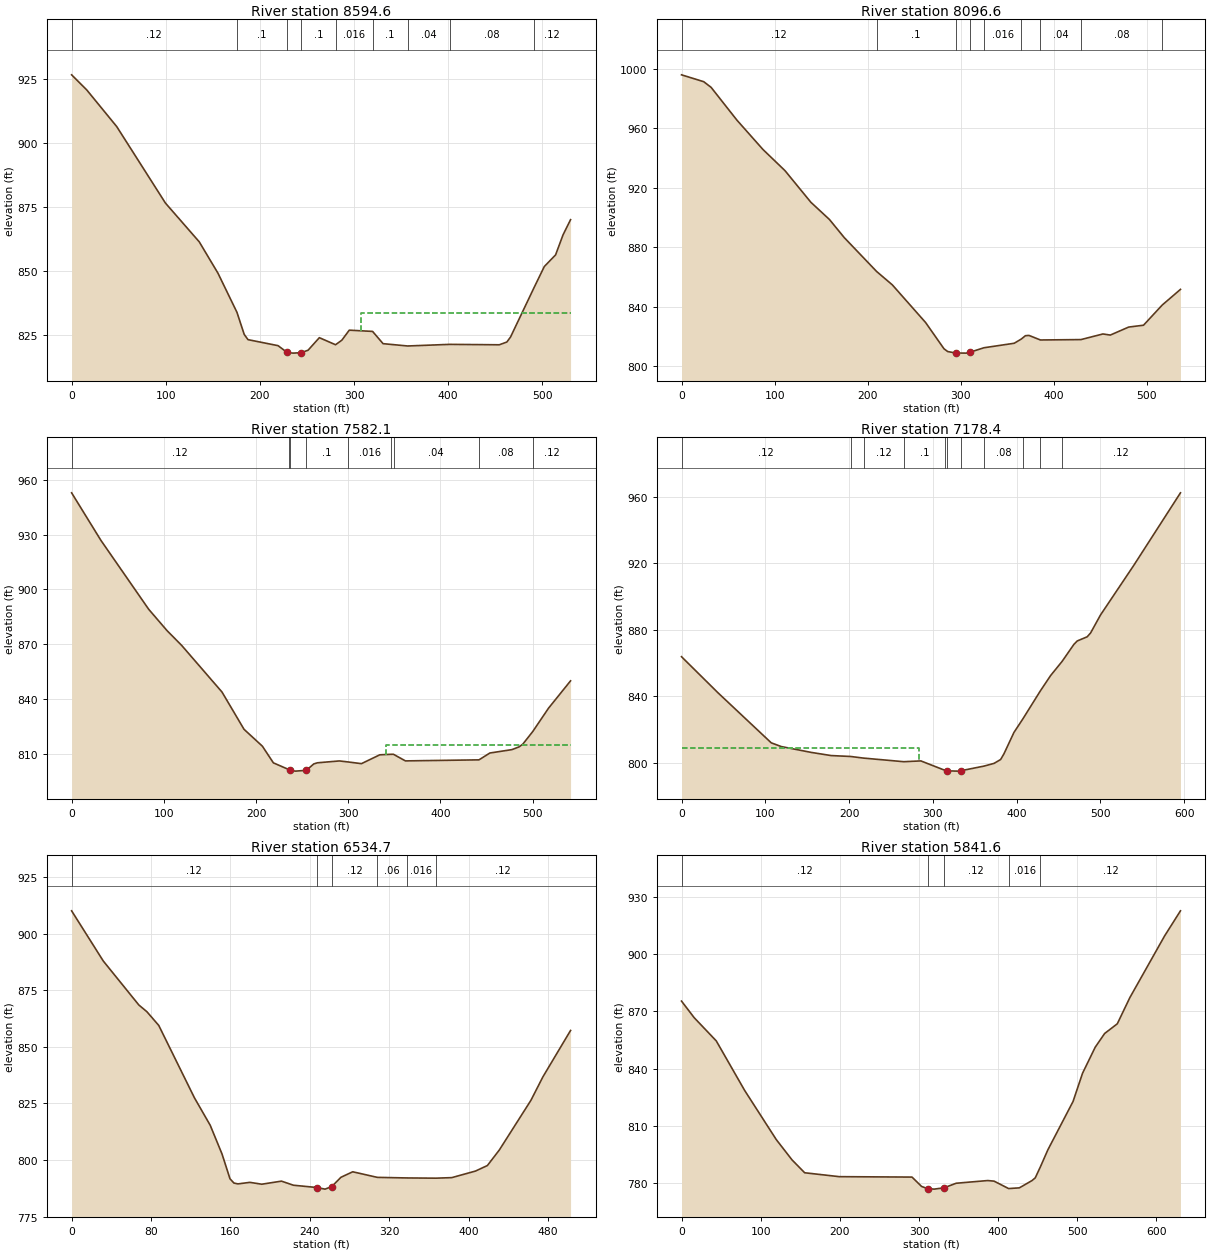
Type RM Length L Ch R = 1 ,8594.6  ,498,498,498.8
XS GIS Cut Line= 3
     1778940.147      394802.192     1779088.886      394619.875
     1779283.658      394398.594
#Sta/Elev= 30
       0  926.56      16  920.69    47.9  906.34    99.7  876.41   135.6  861.26
   155.5  848.99  175.65833.7101   183.4  825.04   187.4  823.01   219.3  820.66
   228.8  818.06   235.3  817.74   243.8  817.91   251.2  818.87   263.2  823.78
  280.41821.0208   287.1   822.8     295  826.72  319.76826.2289   330.9  821.44
  357.04 820.534  401.74821.1635   454.4     821   462.4  822.08   466.3  824.02
  491.15843.2277   502.2   851.6   514.2  856.16   522.1  863.98   530.1  869.92
#Mann= 9 ,-1 , 0
       0     .12       0  175.65      .1       0   228.8    .045       0
   243.8      .1       0  280.41    .016       0  319.76      .1       0
  357.04     .04       0  401.74     .08       0  491.15     .12       0
#XS Ineff= 2 , 0
                          306.95          833.33
Permanent Ineff=
       F       F
Bank Sta=228.8,243.8
XS Rating Curve= 0 ,0
Exp/Cntr=0.3,0.1

Type RM Length L Ch R = 1 ,8096.6  ,509.3,514.5,517.5
XS GIS Cut Line= 3
     1779277.257      395162.509     1779467.116      394927.775
     1779625.712      394755.593
#Sta/Elev= 30
       0  996.02    23.8  991.42    31.8  987.59    59.6  965.51    87.4   945.9
   111.2  931.59     139  910.34   158.9   898.8   174.8  886.63  209.65863.8087
   226.4  854.89   262.2  829.55     282  811.86     286  810.03   294.4  809.06
   305.9  808.97   309.4  809.48  324.85812.5707   357.4   815.6  365.01818.4294
   369.4  820.67   373.3  820.87  385.52817.8108  429.11818.0656   452.7  821.85
   460.6   821.1   480.4  826.49   496.3  827.73   516.3841.2269     536  851.82
#Mann= 9 ,-1 , 0
       0     .12       0  209.65      .1       0   294.4    .045       0
   309.4      .1       0  324.85    .016       0  365.01      .1       0
  385.52     .04       0  429.11     .08       0   516.3     .12       0
Bank Sta=294.4,309.4
XS Rating Curve= 0 ,0
Exp/Cntr=0.3,0.1

Type RM Length L Ch R = 1 ,7582.1  ,402.1,403.8,404
XS GIS Cut Line= 2
     1779575.448      395481.228     1779998.945      395144.445
#Sta/Elev= 30
       0  952.86    31.8  926.82    83.6   889.1   103.4  877.46   119.4  869.29
   163.1  843.78     187  823.37   206.9  814.13   218.8  805.02  235.87801.2605
   236.5  801.18   242.7  800.48   254.6  800.92   262.6  804.42   266.6  805.04
   290.4  806.06  299.43805.5287   314.3  804.57   334.2  809.41  346.88809.6981
  349.08809.6926     362  806.08  441.79806.6513   453.6   810.4   477.4  812.24
   485.4  813.79   489.4  815.31  500.02822.1072   517.2  834.94   541.1  849.91
#Mann= 9 ,-1 , 0
       0     .12       0  235.87      .1       0   236.5    .045       0
   254.6      .1       0  299.43    .016       0  346.88      .1       0
  349.08     .04       0  441.79     .08       0  500.02     .12       0
#XS Ineff= 2 , 0
                          341.21          815.05
Permanent Ineff=
       F       F
Bank Sta=236.5,254.6
XS Rating Curve= 0 ,0
Exp/Cntr=0.3,0.1

Type RM Length L Ch R = 1 ,7178.4  ,664.3,643.6,623
XS GIS Cut Line= 3
     1779837.017      395753.388     1780112.338      395538.677
     1780303.026      395382.562
#Sta/Elev= 30
       0   863.8    43.6  842.05   107.1  811.96     119  809.73   154.7  806.21
   178.5   804.3  202.06803.7386  217.31802.7711  265.34800.6019   285.7  801.08
  314.42795.4155   317.5  795.11   329.3  794.93   333.3  795.15  361.04797.9468
     373  799.58   380.9   801.9   384.9  805.35   396.8  818.19  407.67826.5208
  428.27843.1676   440.6  852.45  454.29860.9619   468.4  871.22   472.4  873.28
   484.3  875.79   488.3  878.08   500.2  888.95   539.9   918.8   595.6  962.43
#Mann= 11 ,-1 , 0
       0     .12       0  202.06     .06       0  217.31     .12       0
  265.34      .1       0  314.42    .016       0   317.5    .045       0
   333.3    .016       0  361.04     .08       0  407.67     .12       0
  428.27     .08       0  454.29     .12       0
#XS Ineff= 2 , 0
          283.21  808.57
Permanent Ineff=
       F       F
Bank Sta=317.5,333.3
XS Rating Curve= 0 ,0
Exp/Cntr=0.3,0.1

Type RM Length L Ch R = 1 ,6534.7  ,671.6,693.2,707.8
XS GIS Cut Line= 2
     1780577.598      396134.533     1780582.975      395631.739
#Sta/Elev= 30
       0  910.04    31.9  887.88    67.8  868.42    75.8   865.5    87.8  859.43
   123.7   827.5   139.7  815.29   151.6  802.59   159.6  791.68   163.6  789.78
   167.6  789.41   179.6  790.09   191.6  789.27   211.5  790.63   223.5  788.83
   247.1  787.81   255.4   787.1   262.1  788.21   271.4  792.33   283.3  794.76
  308.06792.2952  337.59792.0402  367.14791.9393   383.1  792.18     407  795.08
     419  797.53     431  804.38   462.9  826.36   474.9  836.68   502.8  857.19
#Mann= 6 ,-1 , 0
       0     .12       0   247.1    .045       0   262.1     .12       0
  308.06     .06       0  337.59    .016       0  367.14     .12       0
Bank Sta=247.1,262.1
XS Rating Curve= 0 ,0
Exp/Cntr=0.3,0.1

Type RM Length L Ch R = 1 ,5841.6  ,323.1,321.9,320.2
XS GIS Cut Line= 2
     1780925.896      396218.816     1781353.235      395755.556
#Sta/Elev= 30
       0  875.34      16  866.67    43.9  854.52    79.8  828.57   119.7  802.89
   139.6  792.26   155.6  785.52   199.4  783.48   291.2  783.26   303.2  778.38
   311.1  777.19   319.1  776.96   331.6  777.65     347  780.04   386.9  781.45
   394.9  781.13  413.21777.2538   426.8  777.63   442.8  781.45   446.8  782.83
   453.4788.6533   462.7  797.44   494.6  822.82   506.6   837.6   522.6  851.21
   534.5  858.39   550.5  863.47   566.4   877.2   610.3  909.47   630.3  922.58
#Mann= 5 ,-1 , 0
       0     .12       0   311.1    .045       0   331.6     .12       0
  413.21    .016       0   453.4     .12       0
Bank Sta=311.1,331.6
XS Rating Curve= 0 ,0
Exp/Cntr=0.3,0.1

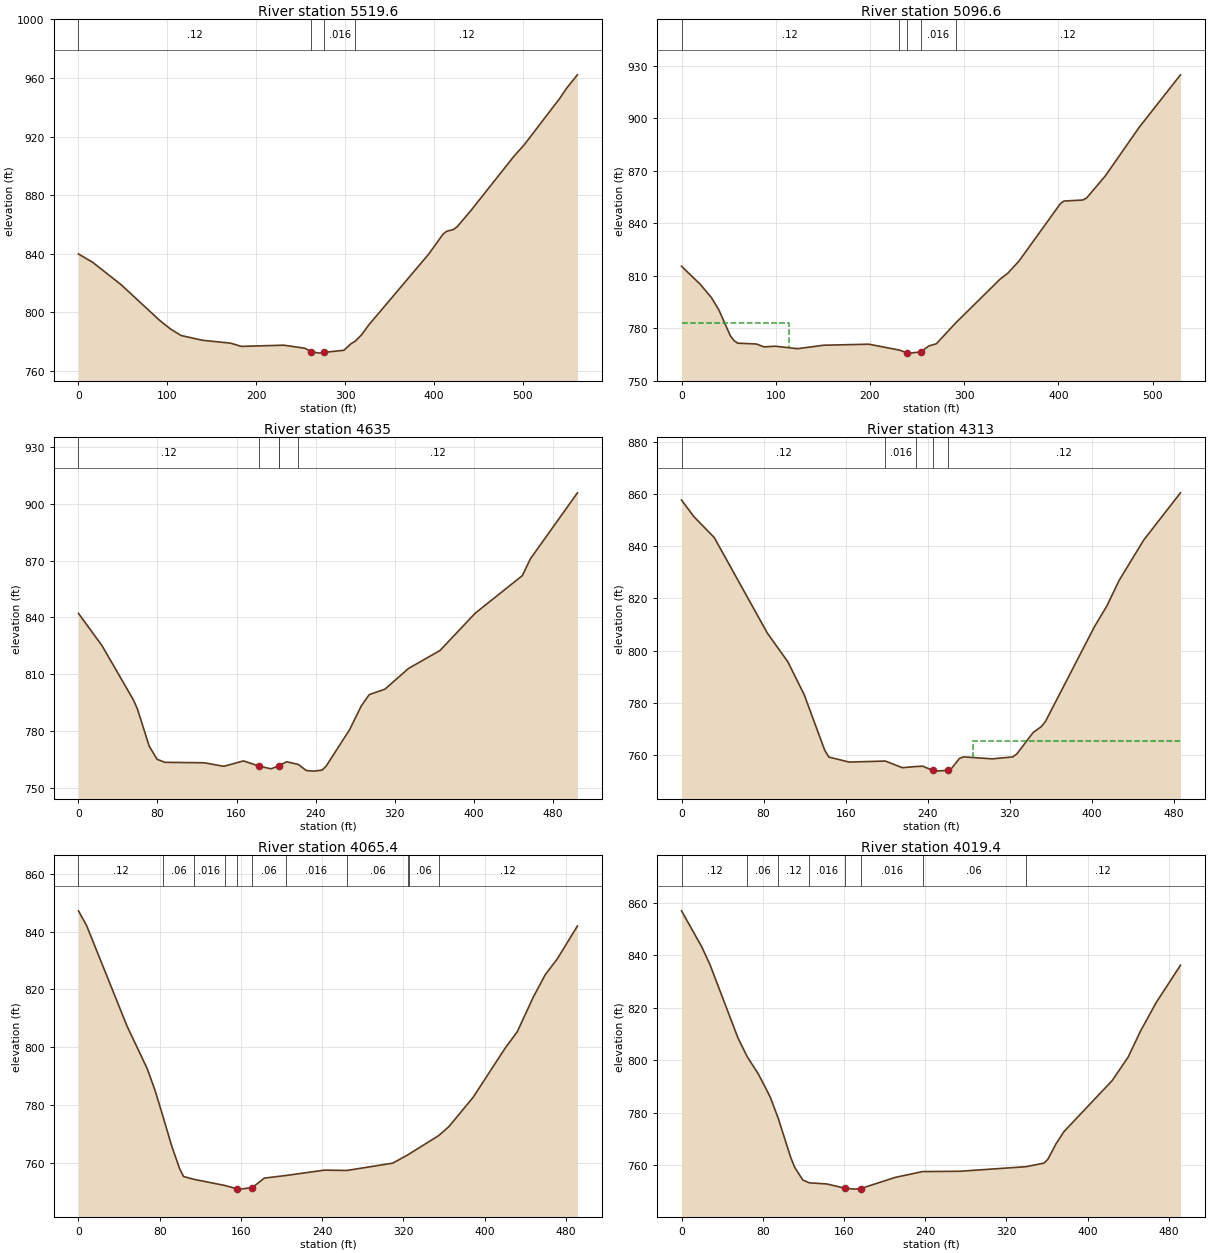
Type RM Length L Ch R = 1 ,5519.6  ,435.1,423,408.6
XS GIS Cut Line= 2
     1781178.744       396366.93      1781584.17      395978.427
#Sta/Elev= 30
       0  839.74    15.9  834.09    47.8  818.85    91.6  794.25   103.5  788.51
   115.5  784.04   139.4   780.8   171.2  778.81   183.2   776.6     231  777.43
   254.9  775.33   261.6  773.09   270.8     772   276.6  772.55   298.7  773.94
   306.6   778.4  311.55780.2189   318.6  784.53   326.6   791.2   394.3   839.8
   410.2  853.25   414.2   855.2   422.1  856.51   426.1  858.31     442  869.72
   489.8  906.35   501.8  914.48   541.6  946.08   549.6  953.27   561.5  962.16
#Mann= 4 ,-1 , 0
       0     .12       0   261.6    .045       0   276.6    .016       0
  311.55     .12       0
Bank Sta=261.6,276.6
XS Rating Curve= 0 ,0
Exp/Cntr=0.3,0.1

Type RM Length L Ch R = 1 ,5096.6  ,468.8,461.6,455.5
XS GIS Cut Line= 3
     1781667.021      396612.682     1781722.505      396372.557
      1781771.56      396093.759
#Sta/Elev= 30
       0  815.37    19.9  805.06    31.8  797.44    39.8  790.26    51.7  775.79
    55.6  772.98    59.6  771.43    79.5  770.95    87.4  769.32    99.4  769.69
   123.2  768.29     151  770.26   198.8  770.84  230.95  767.51     239  765.98
   242.5  765.74     254  766.47   262.4  769.82   270.4  771.08   291.1 783.066
   338.2  808.06   346.1  811.31   358.1  818.31     402   851.1   405.9  852.63
   425.9  853.23   429.9  854.37   449.8  867.02   485.7  894.75   529.5  924.74
#Mann= 5 ,-1 , 0
       0     .12       0  230.95    .016       0     239    .045       0
     254    .016       0   291.1     .12       0
#XS Ineff= 2 , 0
          113.96  782.71
Permanent Ineff=
       F       F
Bank Sta=239,254
XS Rating Curve= 0 ,0
Exp/Cntr=0.3,0.1

Type RM Length L Ch R = 1 ,4635    ,323.1,322,321
XS GIS Cut Line= 2
      1782188.55       396608.83     1782131.463      396106.832
#Sta/Elev= 30
       0  842.17    23.9  825.05    55.7  796.35    59.7   791.6    71.6     772
    79.6  765.04    87.5  763.44   127.3  763.19   147.2  761.33   167.1  764.18
     183   761.4   194.9  760.01   202.9  761.57   203.5  761.78   210.8  763.73
   222.6 762.307   230.7  759.08   238.7  758.78   246.6  759.33   250.6  761.31
   274.5  780.68   286.4  793.31   294.4  799.24   310.3   802.1   334.2  813.07
     366  822.54   401.8  842.33   449.5  862.18   457.5  870.96   505.2  905.91
#Mann= 5 ,-1 , 0
       0     .12       0     183    .045       0   202.9    .016       0
   203.5    .016       0   222.6     .12       0
Bank Sta=183,202.9
XS Rating Curve= 0 ,0
Exp/Cntr=0.3,0.1

Type RM Length L Ch R = 1 ,4313    ,238.8,247.5,255.5
XS GIS Cut Line= 2
     1782502.918      396614.491     1782445.626      396131.418
#Sta/Elev= 30
       0  857.72      12  851.38    31.9  843.34    83.7  806.71   103.7   795.7
   119.6  783.13   139.6  761.87   143.6   759.2   163.5  757.28  198.69757.6732
   215.3  755.13  228.43755.5678   235.2   755.7   244.9   754.1   247.2  753.81
   259.9   754.1   263.2  754.79   271.1  758.71   275.1  759.27     303  758.51
     323  759.26     327  760.43   342.9  768.62   350.9   770.9   354.9  772.89
   402.7  809.21   414.7  817.09   426.6  826.84   450.6  842.34   486.5  860.47
#Mann= 5 ,-1 , 0
       0     .12       0  198.69    .016       0  228.43     .12       0
   244.9    .045       0   259.9     .12       0
#XS Ineff= 2 , 0
                          284.62          765.17
Permanent Ineff=
       F       F
Bank Sta=244.9,259.9
XS Rating Curve= 0 ,0
Exp/Cntr=0.3,0.1

Type RM Length L Ch R = 1 ,4065.4  ,45.1,46,47.1
XS GIS Cut Line= 3
     1782677.345      396587.582     1782711.858      396419.927
     1782777.013      396106.435
#Sta/Elev= 30
       0  847.21       8  842.11    47.8  807.35    67.7   792.6    75.6  784.88
   83.51775.7419    91.6  766.08    99.5  758.11   103.5  755.29  113.66754.3217
  143.82752.2154   156.1  751.05   159.2  750.93   171.1  751.45     183  754.74
  204.14  755.64   242.3   757.5  264.48757.3911   309.5  759.92  324.81762.8706
  325.22762.9789  354.98769.5048   364.9   772.6   388.6  782.66   420.2   799.7
   432.1  805.35   447.9  817.35   459.7  825.12   471.6  830.61   491.4  841.98
#Mann= 11 ,-1 , 0
       0     .12       0   83.51     .06       0  113.66    .016       0
  143.82     .06       0   156.1    .045       0   171.1     .06       0
  204.14    .016       0  264.48     .06       0  324.81     .12       0
  325.22     .06       0  354.98     .12       0
Bank Sta=156.1,171.1
XS Rating Curve= 0 ,0
Exp/Cntr=0.3,0.1

Type RM Length L Ch R = 1 ,4019.4  ,46.9,46,45
XS GIS Cut Line= 3
     1782714.406       396598.14     1782756.363      396432.192
     1782835.438      396121.918
#Sta/Elev= 30
       0  856.95    19.9  843.23    27.9  836.56    55.7  808.37   64.79801.2478
    75.6  794.74    83.6  788.82    87.6  785.68   95.26777.7965   107.5  762.91
   111.5  759.08   119.4  754.29  125.72753.1953   143.3  752.74   161.3  751.09
   171.2  750.78   176.3  750.98   210.7  755.28  237.49757.4722     274  757.59
  339.06759.3297     357   760.7   360.9  762.22   368.8  768.04   376.7  772.74
   424.2  792.22     440  801.22   451.8  810.89   467.6  822.03   491.4  836.18
#Mann= 8 ,-1 , 0
       0     .12       0   64.79     .06       0   95.26     .12       0
  125.72    .016       0   161.3    .045       0   176.3    .016       0
  237.49     .06       0  339.06     .12       0
Bank Sta=161.3,176.3
XS Rating Curve= 0 ,0
Exp/Cntr=0.3,0.1