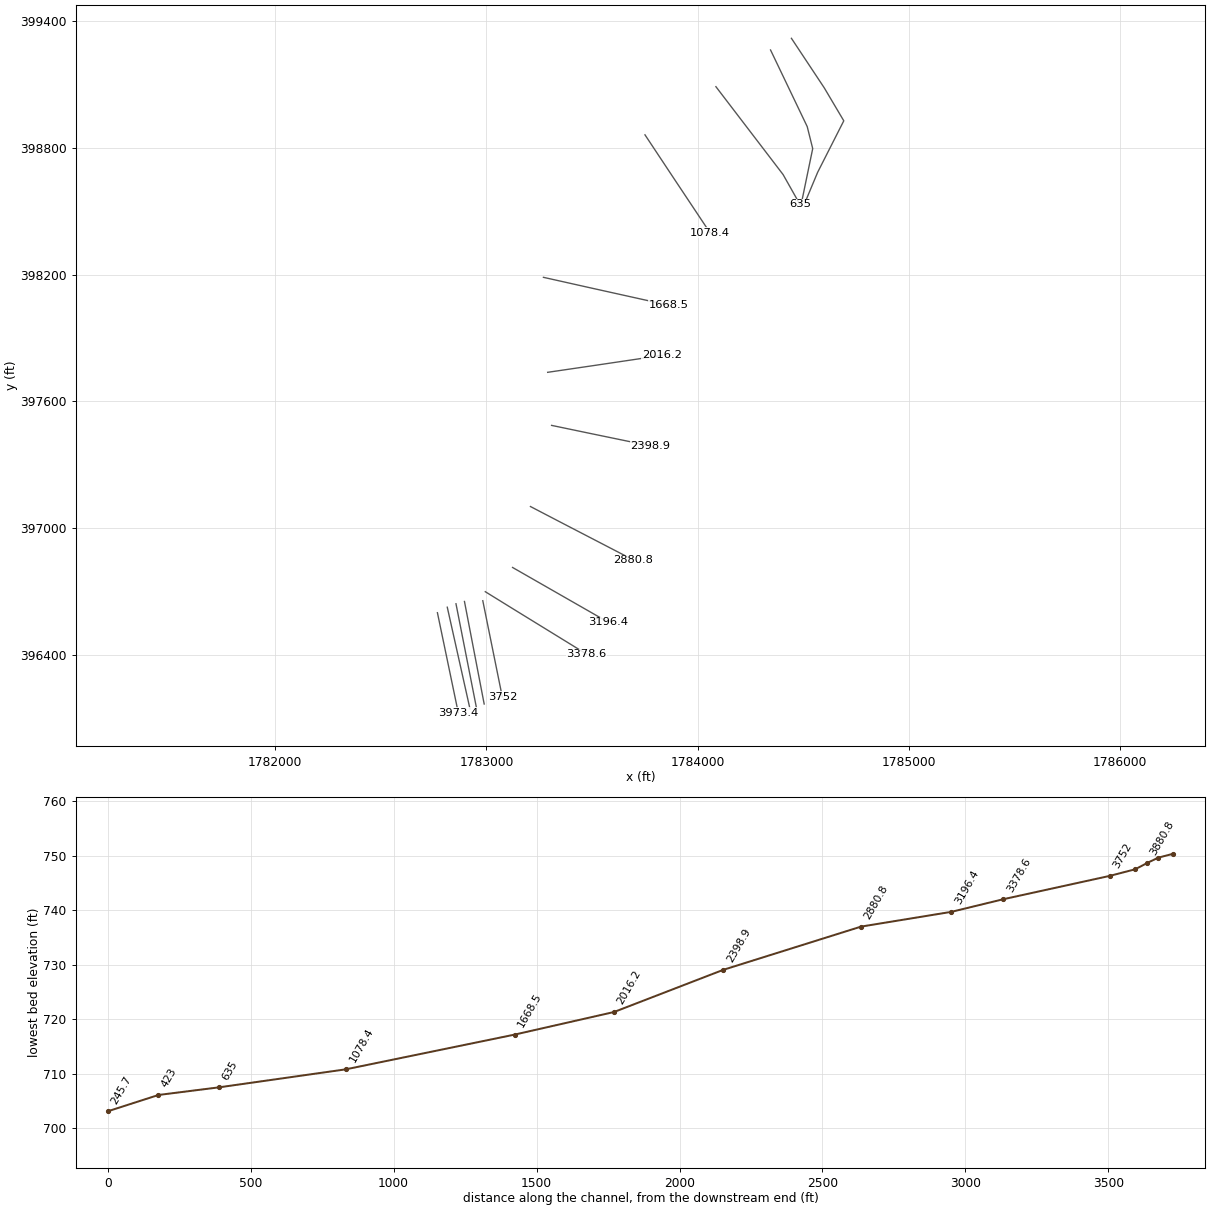
HEC-RAS study SANDLICKCK.prj: SANDLICKCK

--- SANDLICKCK.g01 (geometry) --- (continued)

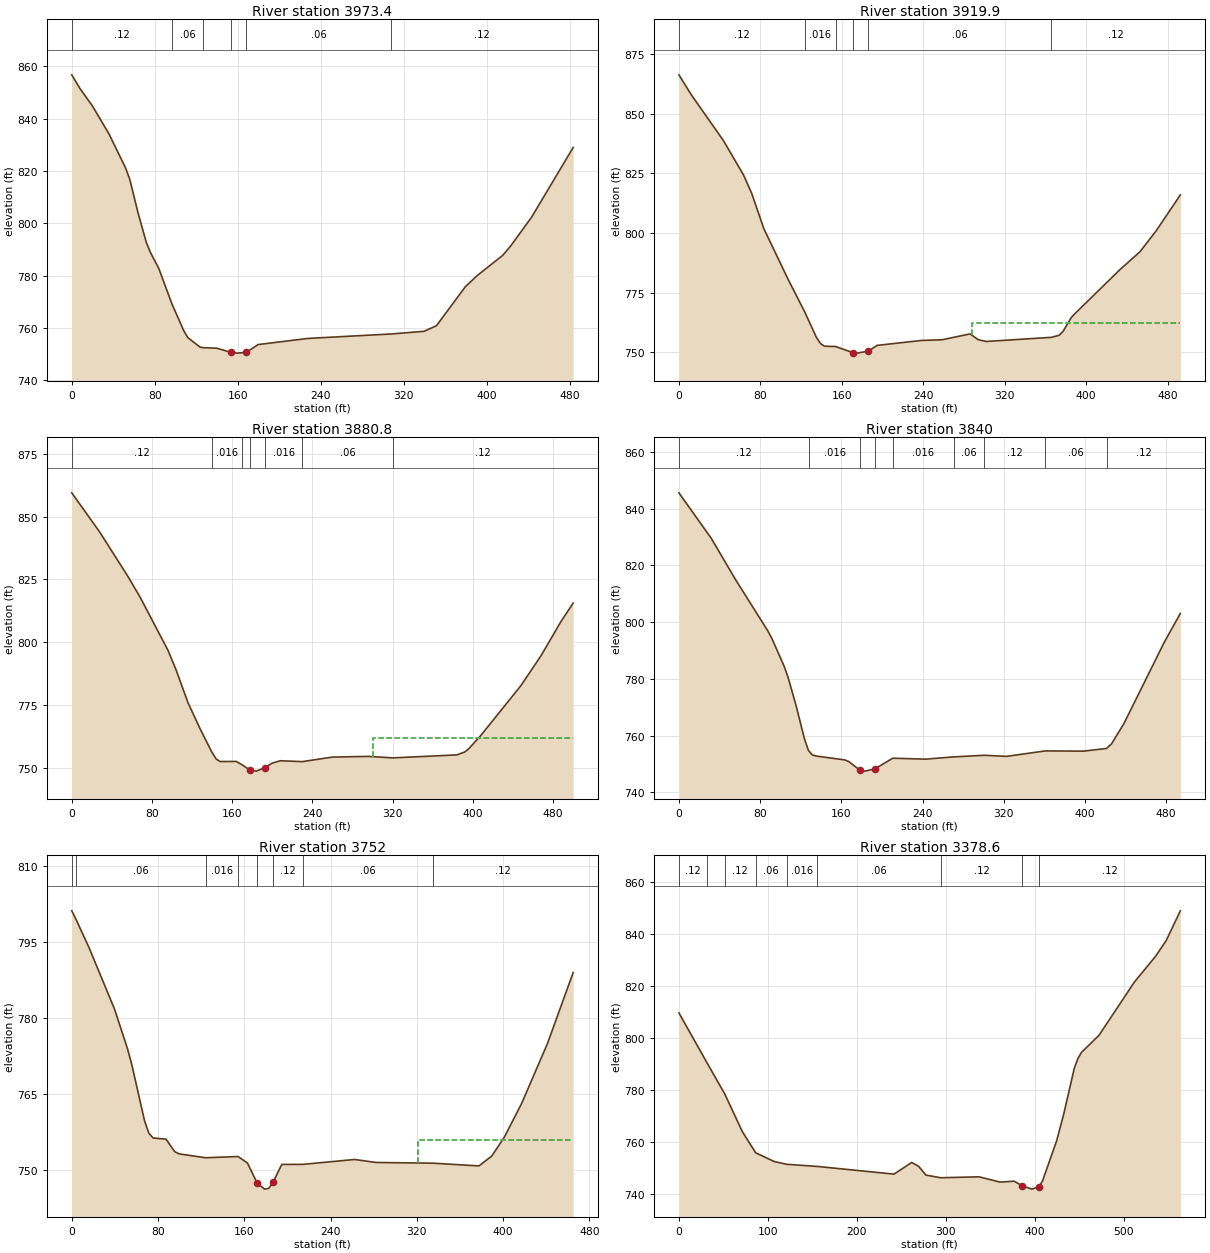
Type RM Length L Ch R = 1 ,3973.4  ,53.2,53.5,53.9
XS GIS Cut Line= 2
     1782768.109      396600.385      1782866.85      396127.295
#Sta/Elev= 30
       0  856.76       8  851.48      20  844.82      36   834.1    51.9  821.14
    55.9  816.86    63.9  803.99    71.9  792.66    75.9  788.81    83.9  782.73
   96.63769.1118   107.8  759.08   111.8  756.31   123.8  752.61  126.81752.4294
   139.8  752.22   153.3  750.66   159.8  750.34   168.3  750.65   179.7  753.62
   227.7  755.96  307.84757.6642   339.5  758.68   351.5   760.8   379.4  775.74
   391.4   780.2   415.4  787.72   423.4  791.49   443.3  802.36   483.3  828.97
#Mann= 6 ,-1 , 0
       0     .12       0   96.63     .06       0  126.81    .016       0
   153.3    .045       0   168.3     .06       0  307.84     .12       0
Bank Sta=153.3,168.3
XS Rating Curve= 0 ,0
Exp/Cntr=0.3,0.1

Type RM Length L Ch R = 1 ,3919.9  ,39.7,39.1,38.5
XS GIS Cut Line= 2
     1782814.767      396626.427     1782922.189      396145.741
#Sta/Elev= 30
       0   866.3    11.9  858.11    43.7  838.73    63.6  824.21    71.5  816.59
    83.4   801.8   107.2  780.59  123.61766.8539     135  756.25     139  753.66
     143   752.5  153.88752.3882   171.2  749.77   174.8  749.61   186.2  750.46
   194.6  752.85   238.3  754.93   258.2  755.19     286  757.67   293.9  755.27
   301.9   754.5  365.73756.2257   373.4  757.08   377.4  758.78   385.3   764.5
   389.3  766.31     433  784.55   452.8  792.09   468.7  800.86   492.5  815.94
#Mann= 6 ,-1 , 0
       0     .12       0  123.61    .016       0  153.88     .06       0
   171.2    .045       0   186.2     .06       0  365.73     .12       0
#XS Ineff= 2 , 0
                          287.73          762.33
Permanent Ineff=
       F       F
Bank Sta=171.2,186.2
XS Rating Curve= 0 ,0
Exp/Cntr=0.3,0.1

Type RM Length L Ch R = 1 ,3880.8  ,40.9,40.8,40.7
XS GIS Cut Line= 2
     1782855.999      396642.703     1782952.571      396152.252
#Sta/Elev= 30
       0  859.51      28  843.83      56   826.2      68  818.06      96  796.74
     104  788.98     116   775.8     128  765.46  139.54756.3127     144  753.45
     148  752.43     164  752.49  169.65 751.182   177.6  749.06     184  748.62
   192.6  750.01     200  751.84     208  752.75  229.85752.4059   259.9  754.22
   295.9  754.49  320.16753.8968   383.9  755.09   391.9  756.26   395.9  757.56
   407.9  762.86   447.9  782.73   467.9  794.63   487.9  808.33   499.9  815.57
#Mann= 7 ,-1 , 0
       0     .12       0  139.54    .016       0  169.65     .06       0
   177.6    .045       0   192.6    .016       0  229.85     .06       0
  320.16     .12       0
#XS Ineff= 2 , 0
                          300.45          761.71
Permanent Ineff=
       F       F
Bank Sta=177.6,192.6
XS Rating Curve= 0 ,0
Exp/Cntr=0.3,0.1

Type RM Length L Ch R = 1 ,3840    ,87.7,88,88.2
XS GIS Cut Line= 2
     1782896.147      396653.554     1782989.463      396168.528
#Sta/Elev= 30
       0  845.54    31.9  829.49    55.8  814.95    87.6  796.89    91.6  794.18
   103.6  784.48   107.6  780.44   115.5  770.46   123.5  759.06   127.5  754.82
   128.5754.4046   131.4   753.2   135.4  752.79   163.3  751.45   167.3  750.86
     178   747.9   183.2  747.49     193  748.27  210.63752.0436     243  751.71
  270.79752.5092  300.87753.0751   322.6  752.69  361.02754.6159   398.3  754.53
  421.18755.4772   426.2  757.14   438.2  764.16     478  792.84   493.9  803.05
#Mann= 9 ,-1 , 0
       0     .12       0   128.5    .016       0     178    .045       0
     193     .12       0  210.63    .016       0  270.79     .06       0
  300.87     .12       0  361.02     .06       0  421.18     .12       0
Bank Sta=178,193
XS Rating Curve= 0 ,0
Exp/Cntr=0.3,0.1

Type RM Length L Ch R = 1 ,3752    ,354.4,373.4,391.5
XS GIS Cut Line= 2
     1782982.953      396657.026     1783075.401      396201.297
#Sta/Elev= 30
       0   801.2    3.63799.6754    15.9  794.01    39.7   781.8    51.7     774
    55.6  770.95    67.6   759.7    71.5  757.34    75.5  756.37    87.4  756.16
    95.4  753.71    99.4  753.25  124.18  752.48  154.32752.7232     163  751.43
   171.9   747.5   178.8  746.29   182.8  746.45   186.9  747.74   194.8  751.16
   214.6  751.18   262.3  752.14   282.2  751.55  335.15751.4072   377.6  750.87
   389.5  752.81   401.4  756.63   417.3  763.23   441.2  775.03     465  789.02
#Mann= 8 ,-1 , 0
       0     .12       0    3.63     .06       0  124.18    .016       0
  154.32     .12       0   171.9    .045       0   186.9     .12       0
   214.6     .06       0  335.15     .12       0
#XS Ineff= 2 , 0
                          321.37          755.92
Permanent Ineff=
       F       F
Bank Sta=171.9,186.9
XS Rating Curve= 0 ,0
Exp/Cntr=0.3,0.1

Type RM Length L Ch R = 1 ,3378.6  ,181,182.2,182.4
XS GIS Cut Line= 3
     1782994.759      396699.745     1783139.615      396610.326
     1783474.659      396404.383
#Sta/Elev= 30
       0  809.64   31.88790.2999   51.49778.5455    71.3  764.05    86.2 755.964
   106.9  752.62  120.91751.5342  155.62750.7103   241.7  747.76   261.6  752.23
   269.5  750.73   277.5   747.4  294.31746.3591   337.1  746.73   360.9   744.7
   376.8  745.05   385.7  743.27   396.7     742   404.6  742.94   408.6  745.12
   424.5  760.56   432.4  770.74   444.3  788.34   448.3  792.06   452.3  794.44
   472.1  801.05   511.9  821.49   535.7  831.37   547.6  837.41   563.5  848.81
#Mann= 9 ,-1 , 0
       0     .12       0   31.88     .06       0   51.49     .12       0
    86.2     .06       0  120.91    .016       0  155.62     .06       0
  294.31     .12       0   385.7    .045       0   404.6     .12       0
Bank Sta=385.7,404.6
XS Rating Curve= 0 ,0
Exp/Cntr=0.3,0.1

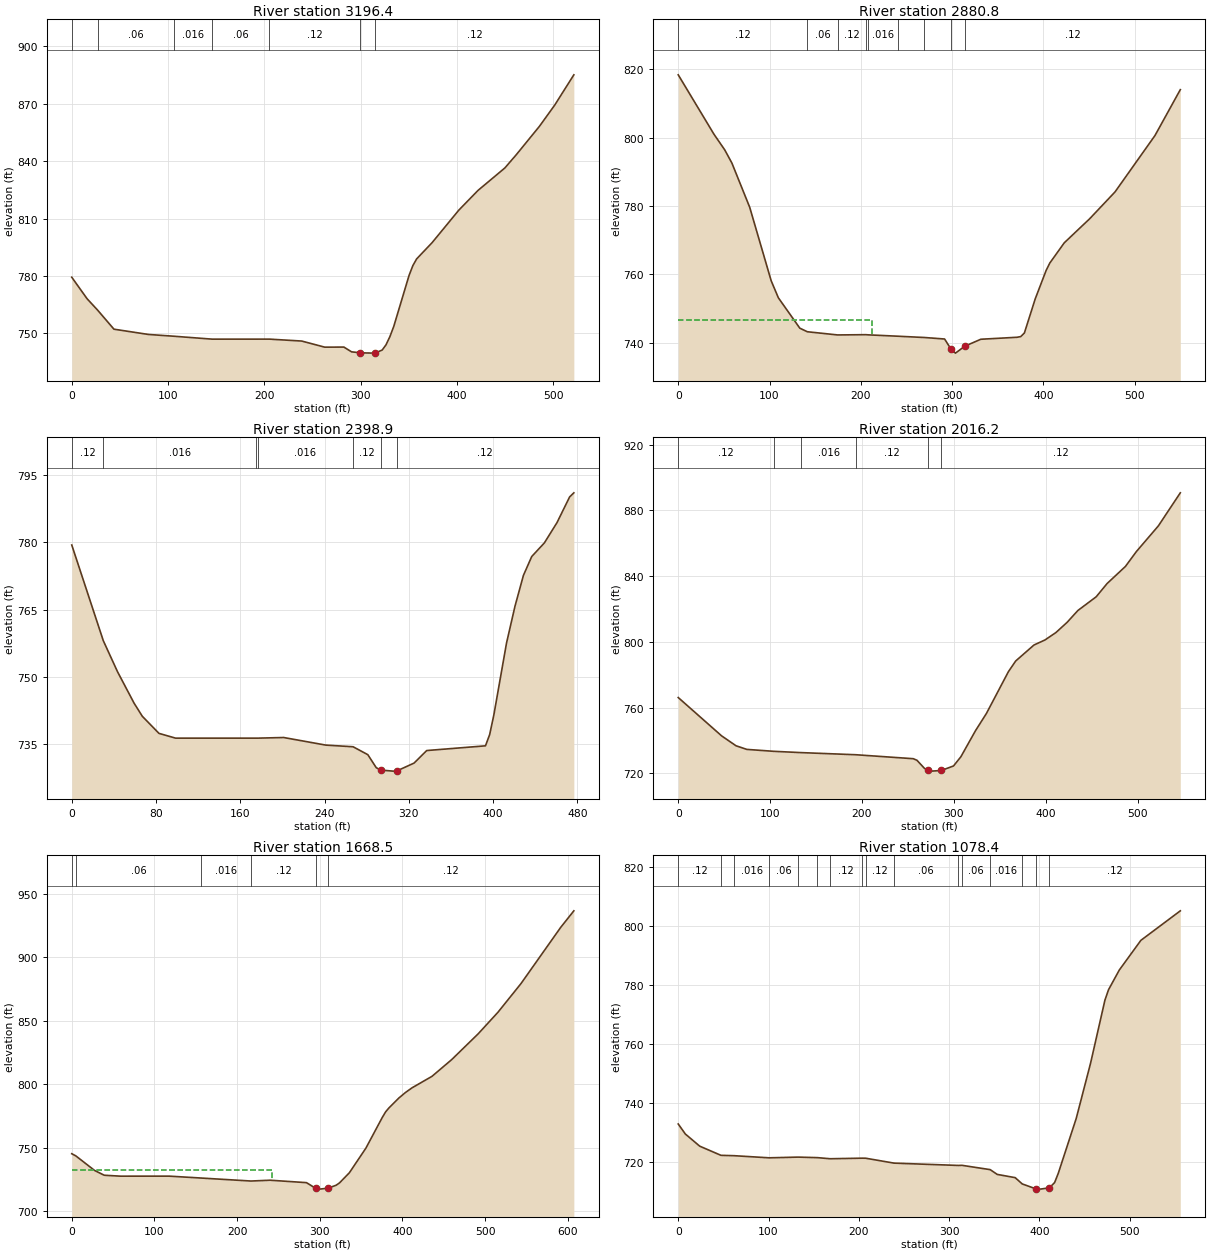
Type RM Length L Ch R = 1 ,3196.4  ,314.1,315.5,316.1
XS GIS Cut Line= 2
     1783123.953      396814.416     1783576.327      396555.625
#Sta/Elev= 30
       0  779.35    15.9  768.11   26.73 762.215    43.8  752.19    79.6  749.44
   105.8  748.52   145.7746.9875  205.18746.9986   238.7  745.99   262.6   742.8
   282.5  742.84   290.4  740.36   299.7  739.84   314.3  739.68   314.7  739.71
   322.2  741.27   326.2  744.01   330.2  748.26   334.2  753.54   350.1  780.24
   354.1  785.44     358  788.93     374  797.39   401.8  814.42   421.7  824.72
   449.6  836.47   461.5  843.42   485.4  858.18   501.3  869.29   521.2  885.15
#Mann= 7 ,-1 , 0
       0     .12       0   26.73     .06       0   105.8    .016       0
   145.7     .06       0  205.18     .12       0   299.7    .045       0
   314.7     .12       0
Bank Sta=299.7,314.7
XS Rating Curve= 0 ,0
Exp/Cntr=0.3,0.1

Type RM Length L Ch R = 1 ,2880.8  ,475.9,481.9,488.9
XS GIS Cut Line= 3
     1783208.594      397102.745     1783344.067      397032.187
     1783696.724      396849.365
#Sta/Elev= 30
       0   818.4    39.2     801    50.9  796.46    58.8  792.58    78.3  779.65
   101.8  758.16   109.7  753.16   133.2  744.28   141.4743.2367   174.6   742.3
  205.54742.3772  207.87742.3306  241.14741.9206  269.71741.5493   291.8  741.11
   298.9  738.11   303.7  736.98   313.9  739.01   331.5  741.04   371.2  741.62
   375.2  741.82   379.2  742.88   391.1  752.88     403  761.16     407  763.32
   422.9  769.26   450.7  776.29   478.5  784.15   522.2  800.62     550  814.06
#Mann= 9 ,-1 , 0
       0     .12       0   141.4     .06       0   174.6     .12       0
  205.54     .06       0  207.87    .016       0  241.14     .06       0
  269.71     .12       0   298.9    .045       0   313.9     .12       0
#XS Ineff= 2 , 0
          212.66  746.79
Permanent Ineff=
       F       F
Bank Sta=298.9,313.9
XS Rating Curve= 0 ,0
Exp/Cntr=0.3,0.1

Type RM Length L Ch R = 1 ,2398.9  ,374.9,382.7,389.7
XS GIS Cut Line= 3
       1783308.7      397486.576     1783497.903      397447.137
     1783775.436      397389.835
#Sta/Elev= 30
       0  779.38   29.93758.0901    43.4   751.2    59.2  744.17      67  741.26
    82.8  737.46    98.6   736.4  174.68   736.4  176.64   736.4   201.2  736.54
   241.2  734.85  267.12 734.483   281.1  732.72   289.1  729.82   293.6  729.29
     305  729.06   308.6   729.1     325  730.85     337  733.64   392.8  734.69
   396.8  737.21   400.8  741.63   412.8  757.58   420.8  765.74   428.8   772.6
   436.7  776.81   448.7  779.84   460.7  784.36   472.7  790.08   476.7  790.99
#Mann= 7 ,-1 , 0
       0     .12       0   29.93    .016       0  174.68     .12       0
  176.64    .016       0  267.12     .12       0   293.6    .045       0
   308.6     .12       0
Bank Sta=293.6,308.6
XS Rating Curve= 0 ,0
Exp/Cntr=0.3,0.1

Type RM Length L Ch R = 1 ,2016.2  ,355.9,347.7,339.2
XS GIS Cut Line= 3
     1783290.163      397737.636     1783507.931      397769.561
     1783830.863      397817.529
#Sta/Elev= 30
       0   766.1    47.2  742.79    62.9  736.75    74.7  734.54  103.96733.3737
  133.81732.5869  193.51731.2903   255.9  728.88   259.9  727.92   267.9   723.1
   271.4  721.81   275.8  721.32   286.4  721.71   299.7  724.47   307.7  730.05
   323.6   745.9   335.6  756.49   359.4  781.79   367.4  788.35   387.3  798.07
   399.3  801.15   411.2  805.66   423.2  811.77   435.1  819.07     455   827.4
   466.9  835.48   486.8  845.85   498.8  854.95   522.7  870.55   546.6  890.68
#Mann= 6 ,-1 , 0
       0     .12       0  103.96     .06       0  133.81    .016       0
  193.51     .12       0   271.4    .045       0   286.4     .12       0
Bank Sta=271.4,286.4
XS Rating Curve= 0 ,0
Exp/Cntr=0.3,0.1

Type RM Length L Ch R = 1 ,1668.5  ,607.3,590.1,572.7
XS GIS Cut Line= 3
     1783270.101      398187.013     1783500.411      398135.451
     1783863.117      398054.973
#Sta/Elev= 30
       0   745.1     4.9 743.395    27.5  731.95    39.3  728.13      59   727.4
     118  727.42  156.23725.9366  216.77723.5641     240   724.2     284  722.29
   295.4  717.71   299.9  717.18   310.4  717.97   319.9  720.26   323.9  722.06
   335.9  730.09   355.9  749.52   375.8  773.81   379.8  778.15   383.8  781.24
   395.8  789.04   403.8   793.4   411.8  797.11   435.8   806.1   459.7  819.32
   491.7  839.63   515.7  856.68   543.6  879.33   591.6  923.61   607.5  936.66
#Mann= 6 ,-1 , 0
       0     .12       0     4.9     .06       0  156.23    .016       0
  216.77     .12       0   295.4    .045       0   310.4     .12       0
#XS Ineff= 2 , 0
          242.57  732.14
Permanent Ineff=
       F       F
Bank Sta=295.4,310.4
XS Rating Curve= 0 ,0
Exp/Cntr=0.3,0.1

Type RM Length L Ch R = 1 ,1078.4  ,441.2,443.4,444.9
XS GIS Cut Line= 3
     1783750.843      398861.126     1783891.232      398649.505
     1784058.724      398398.065
#Sta/Elev= 30
       0  732.89     7.9  729.49    23.8  725.38   47.32 722.274   61.85722.1506
  100.75 721.429  132.74721.6689  154.17721.4899  168.19721.1152  203.63721.3074
   207.6 721.293  239.08719.6298  310.04718.8466  314.29718.8862  345.53717.4237
   353.3  715.81   373.2  714.71  381.02712.5803   396.2  710.91     401  710.82
   411.2  711.27   416.9  713.06   420.9  716.15   440.8  734.75   456.7  753.49
   472.6  774.86   476.6   778.4   488.5  785.05   512.4  795.12   556.1  805.13
#Mann= 16 ,-1 , 0
       0     .12       0   47.32     .06       0   61.85    .016       0
  100.75     .06       0  132.74    .016       0  154.17     .06       0
  168.19     .12       0  203.63    .016       0   207.6     .12       0
  239.08     .06       0  310.04    .016       0  314.29     .06       0
  345.53    .016       0  381.02     .12       0   396.2    .045       0
   411.2     .12       0
Bank Sta=396.2,411.2
XS Rating Curve= 0 ,0
Exp/Cntr=0.3,0.1

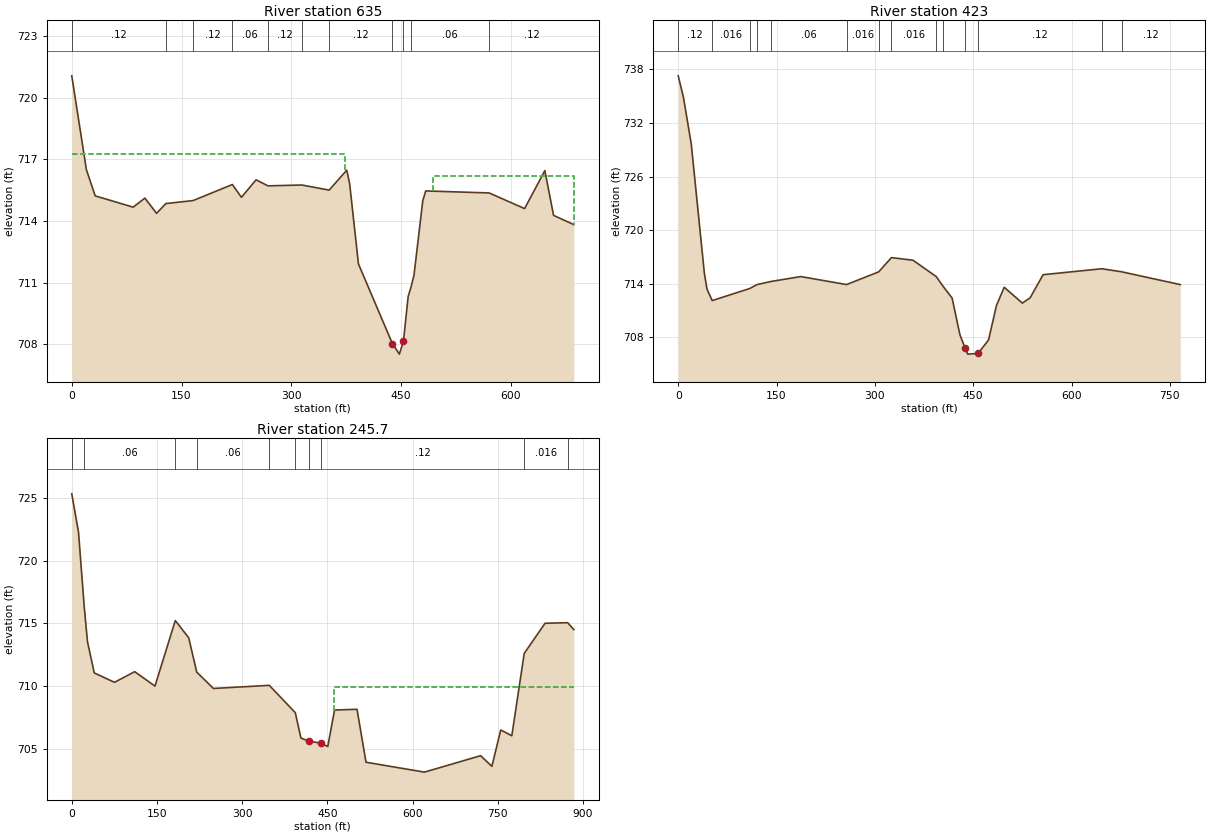
Type RM Length L Ch R = 1 ,635     ,221.9,211.9,202.7
XS GIS Cut Line= 3
     1784086.685      399088.883     1784404.828      398673.085
     1784484.689      398531.592
#Sta/Elev= 30
       0  721.06      20  716.49      32  715.22    83.9  714.67    99.9  715.11
   115.9  714.37  128.55714.8444  165.74714.9906  219.46715.7715   231.8  715.15
   251.8     716  268.06715.7074   314.5 715.747   351.7   715.5   375.7  716.47
   379.7  715.81   391.7  711.91   438.2  708.02   447.6  707.52   453.2  708.15
   459.6  710.32  463.26710.7501   467.6  711.36   479.6  714.98   483.6  715.46
  570.31715.3618   618.7   714.6   646.4  716.45   658.3  714.27     686  713.82
#Mann= 11 ,-1 , 0
       0     .12       0  128.55     .06       0  165.74     .12       0
  219.46     .06       0  268.06     .12       0   314.5    .016       0
   351.7     .12       0   438.2    .045       0   453.2     .12       0
  463.26     .06       0  570.31     .12       0
#XS Ineff= 2 , 0
          373.94  717.26  493.84          716.19
Permanent Ineff=
       F       F
Bank Sta=438.2,453.2
XS Rating Curve= 0 ,0
Exp/Cntr=0.3,0.1

Type RM Length L Ch R = 1 ,423     ,170.1,177.4,183.9
XS GIS Cut Line= 4
     1784345.366      399262.495     1784518.977      398900.081
     1784545.019      398795.915     1784492.935      398544.613
#Sta/Elev= 30
       0  737.27       8  734.84    19.9  729.62    39.8  715.21    43.8  713.41
   51.76712.1143  109.21 713.465  120.12 713.904  141.96714.2573     187   714.8
  256.85713.9069  305.71715.3248  325.22716.9217   358.1  716.63  393.58714.7984
  403.81713.7344   417.8  712.39   429.7  708.29   437.7  706.78   441.6  706.12
   457.5   706.2   473.4  707.71   485.4  711.56   497.3   713.6     525  711.83
   536.9  712.43   556.6  715.01  646.09715.6766  676.26715.3385   765.9   713.9
#Mann= 14 ,-1 , 0
       0     .12       0   51.76    .016       0  109.21     .06       0
  120.12    .016       0  141.96     .06       0  256.85    .016       0
  305.71     .06       0  325.22    .016       0  393.58     .06       0
  403.81     .12       0   437.7    .045       0   457.5     .12       0
  646.09    .016       0  676.26     .12       0
Bank Sta=437.7,457.5
XS Rating Curve= 0 ,0
Exp/Cntr=0.3,0.1

Type RM Length L Ch R = 1 ,245.7   ,253.8,245.7,237.3
XS GIS Cut Line= 5
     1784444.183      399317.753     1784599.565      399083.533
     1784692.154      398927.425     1784568.456      398683.936
     1784511.164      398547.217
#Sta/Elev= 30
       0  725.32    11.9  722.26   21.98716.2838    27.7  713.52    39.6  711.04
    75.2  710.29   110.8  711.14   146.5  709.99  182.27715.2145   205.9  713.84
  219.95711.1094   249.4   709.8  347.69710.0498  393.56707.8688   403.4  705.85
   417.2   705.6   438.9  705.44   450.7  705.17   462.6  708.08   502.2  708.14
     518  703.92   620.9  703.13   719.8  704.44   739.6  703.59   755.2  706.49
   774.7  706.03  796.54 712.594   833.2     715  872.96715.0444   883.9   714.5
#Mann= 10 ,-1 , 0
       0     .12       0   21.98     .06       0  182.27    .016       0
  219.95     .06       0  347.69    .016       0  393.56     .12       0
   417.2    .045       0   438.9     .12       0  796.54    .016       0
  872.96     .12       0
#XS Ineff= 2 , 0
                          462.41          709.93
Permanent Ineff=
       F       F
Bank Sta=417.2,438.9
XS Rating Curve= 0 ,0
Exp/Cntr=0.3,0.1

Chan Stop Cuts=-1
Use User Specified Reach Order=0
Composite Channel Slope=5